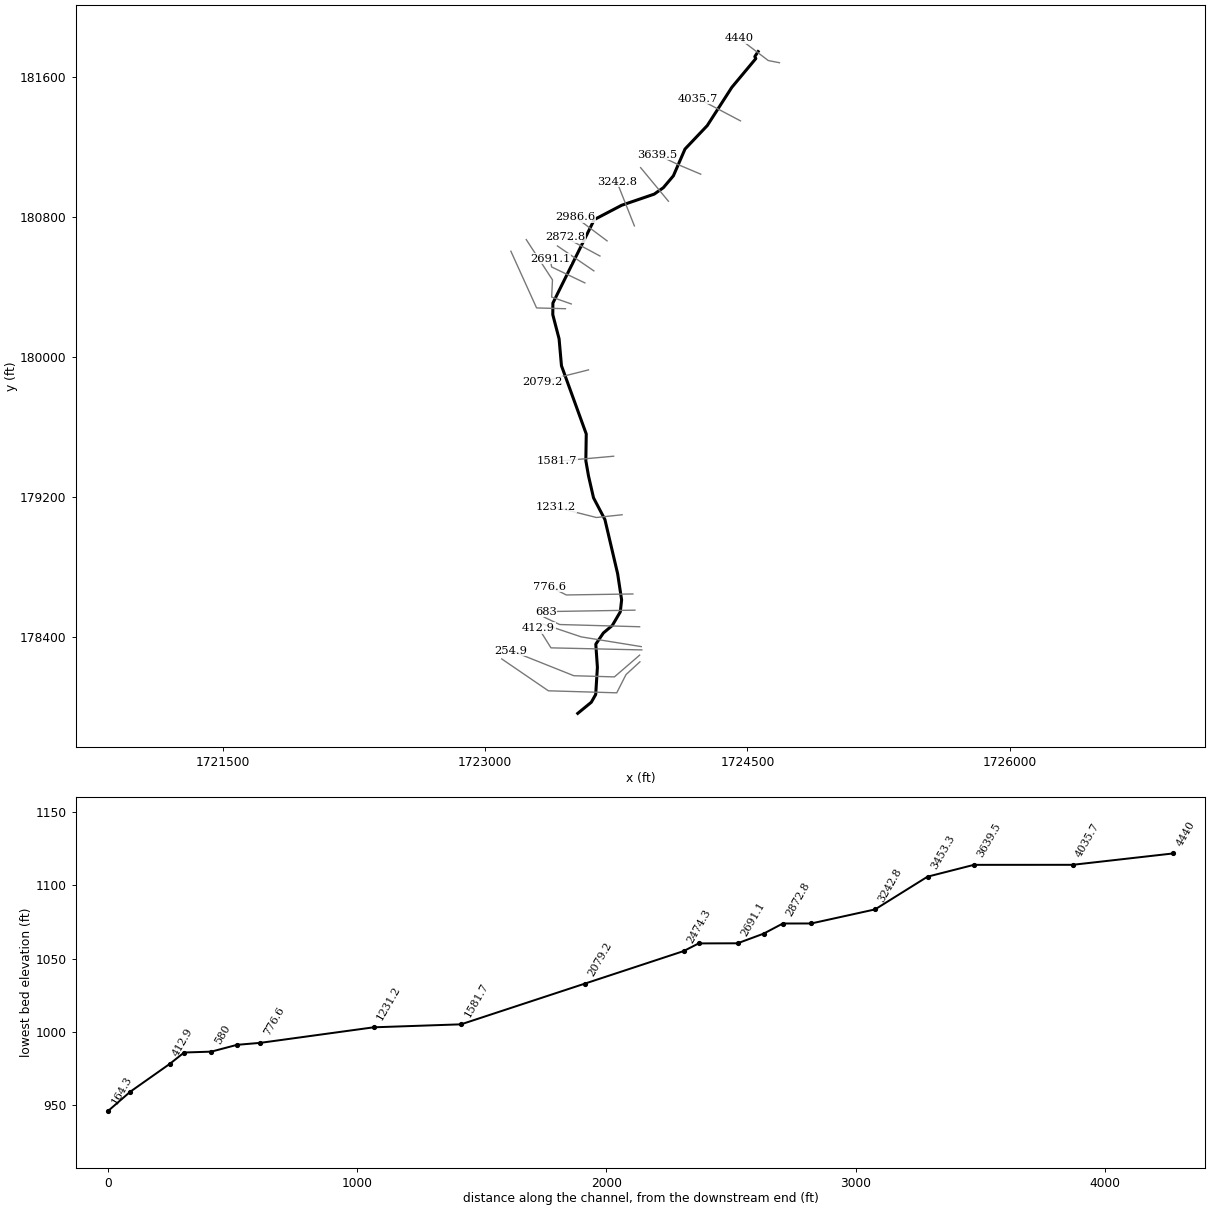
--- War Branch.prj (project) ---

Proj Title=War Branch
Current Plan=p01
Default Exp/Contr=0,0
English Units
Geom File=g01
Flow File=f01
Plan File=p01
BEGIN DESCRIPTION:
END DESCRIPTION:
DSS Export Rating Curves= 0
DSS Export Rating Curve Sorted= 0
DSS Export Volume Flow Curves= 0
DXF OffsetX= 0
DXF OffsetY= 0
DXF ScaleX= 0
DXF ScaleY= 0

--- War Branch.p01 (plan) ---

Plan Title=Floodplain
Program Version=4.00
Geom File=g01
Flow File=f01
K Sum by GR=0
Std Step Tol=0.01
Critical Tol=0.01
Num of Std Step Trials=20
Max Error Tol=0.3
Flow Tol Ratio=0.001
Split Flow NTrial=30
Split Flow Tol=0.02
Split Flow Ratio=0.02
Log Output Level=0
Friction Slope Method=1
Unsteady Friction Slope Method=2
Unsteady Bridges Friction Slope Method=1
Global Log Level=0
CheckData=False
Run HTab=0
Run UNet=0
Run PostProcess=0
UNET Theta=0
UNET Theta Warmup=0
UNET ZTol=0
UNET ZSATol=0
UNET MxIter=0
UNET MaxInSteps=0
UNET DtIC=0
UNET DtMin=0
UNET MaxCRTS=0
UNET WFStab=0
UNET SFStab=0
UNET WFX=0
UNET SFX=0
UNET DSS MLevel=0
UNET DZMax Abort=0
UNET Convert EG Bridges=0
UNET Use Existing IB Tables=0
UNET Froude Limit=0
UNET Froude Power=0
Write IC File=0
Echo Input=False
Echo Output=False
Write Detailed=0

--- War Branch.f01 (steady flow) ---

Flow Title=NFF Regression Equation
Program Version=4.00
Number of Profiles=1
Profile Names=P100yr
River Rch & RM=War Branch,Main      ,4440
574.0313
River Rch & RM=War Branch,Main      ,2986.6
607.7802
River Rch & RM=War Branch,Main      ,2691.1
842.3672
River Rch & RM=War Branch,Main      ,254.9
917.6906
Boundary for River Rch & Prof#=War Branch,Main      ,1
Up Type=0
Dn Type=3
Dn Slope=0.165619

--- War Branch.g01 (geometry) ---

Geom Title=Geometry
Program Version=4.00

River Reach=War Branch      ,Main
Reach XY= 30
     1724560.919      181743.919     1724541.975       181715.28
     1724547.773      181703.989     1724410.579      181539.487
      1724270.07      181320.731     1724143.186      181187.067
     1724076.631      181033.865     1724019.257      180965.996
     1723967.014      180929.178     1723780.802      180865.521
      1723624.61      180783.768      1723388.04      180306.652
     1723387.487      180240.245     1723423.411      180102.251
     1723437.031      179948.616      1723578.68      179558.537
     1723576.295      179405.637     1723591.429      179319.373
     1723620.184       179193.76      1723685.26       179069.66
     1723758.093      178759.601     1723780.794      178610.153
     1723773.227      178542.049     1723727.825      178464.487
     1723676.536       178421.24     1723633.216      178357.245
     1723642.422      178224.857     1723632.616      178069.588
     1723607.555      178025.459     1723530.021      177961.786

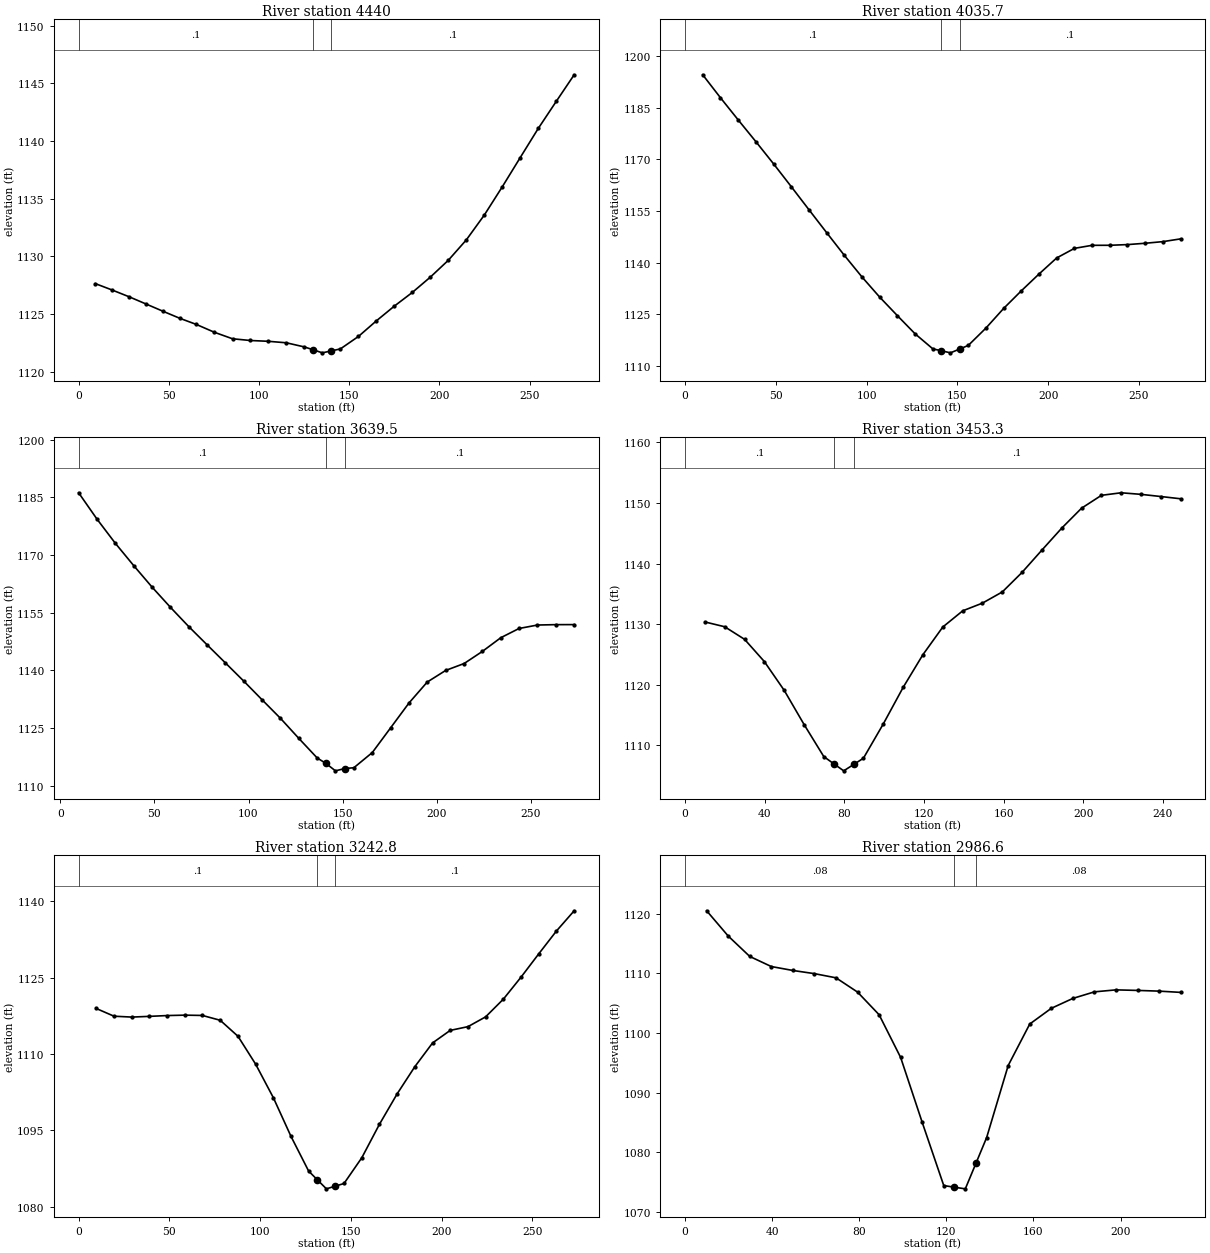
Type RM Length L Ch R = 1 ,4440    ,400.4,404.3,406.7
XS GIS Cut Line= 3
     1724682.865      181680.059     1724618.759      181692.666
     1724452.163       181819.55
#Sta/Elev= 30
     9.3 1127.62    18.7 1127.06      28 1126.48    37.3 1125.86    46.7 1125.23
      56 1124.62    65.3 1124.08    75.3  1123.4    85.3 1122.84    95.2 1122.69
   105.2 1122.62   115.2 1122.49   125.2 1122.13   130.1 1121.88   135.1 1121.62
   140.1 1121.79   145.1 1121.96   155.1 1123.04   165.1  1124.4     175 1125.67
     185 1126.86     195 1128.19   204.9 1129.64   214.9 1131.41   224.9 1133.57
   234.9 1136.03   244.8 1138.55   254.8 1141.08   264.8 1143.43   274.7 1145.73
#Mann= 3 , 0 , 0
       0      .1       0   130.1    .045       0   140.1      .1       0
Bank Sta=130.1,140.1
XS Rating Curve= 0 ,0
Exp/Cntr=0.3,0.1

Type RM Length L Ch R = 1 ,4035.7  ,394.9,396.2,397
XS GIS Cut Line= 3
     1724459.839      181347.999     1724339.121      181411.712
     1724218.403      181475.426
#Sta/Elev= 30
     9.7 1194.59    19.5 1187.91    29.2 1181.52      39 1175.17    48.8 1168.69
    58.5  1162.1    68.2 1155.43      78 1148.74    87.7 1142.18    97.5 1135.85
   107.2 1130.03     117 1124.62   126.7 1119.38   136.5    1115   141.2 1114.45
   146.2 1113.85   151.2 1114.95     156    1116   165.7 1121.02   175.5 1126.75
   185.2 1131.84     195 1136.75   204.7  1141.4   214.5 1144.19   224.2 1145.07
     234 1145.08   243.7 1145.28   253.5 1145.67   263.2 1146.14     273 1146.94
#Mann= 3 , 0 , 0
       0      .1       0   141.2    .045       0   151.2      .1       0
Bank Sta=141.2,151.2
XS Rating Curve= 0 ,0
Exp/Cntr=0.3,0.1

Type RM Length L Ch R = 1 ,3639.5  ,195.4,186.2,177.5
XS GIS Cut Line= 3
     1724232.988      181043.233     1724107.276       181096.35
     1723983.806      181154.913
#Sta/Elev= 30
     9.7  1186.2    19.5 1179.32    29.2 1173.06      39 1167.23    48.7 1161.67
    58.5 1156.39    68.2 1151.39      78 1146.62    87.7 1141.93    97.5 1137.17
   107.2 1132.33     117 1127.49   126.7  1122.3   136.5 1117.18   141.2 1115.75
   146.2 1113.83   151.2 1114.43     156 1114.64   165.8 1118.59   175.5    1125
   185.3 1131.49     195 1136.94   204.8 1139.96   214.6 1141.76   224.3 1144.91
   234.1 1148.48   243.8 1150.88   253.6 1151.78   263.4 1151.88   273.1 1151.89
#Mann= 3 , 0 , 0
     9.7      .1       0   141.2    .045       0   151.2      .1       0
Bank Sta=141.2,151.2
XS Rating Curve= 0 ,0
Exp/Cntr=0.3,0.1

Type RM Length L Ch R = 1 ,3453.3  ,216.8,210.5,204.2
XS GIS Cut Line= 2
     1724048.266      180888.745     1723889.418      181080.523
#Sta/Elev= 27
      10 1130.35    19.9 1129.56    29.9 1127.48    39.8 1123.82    49.8 1119.06
    59.8 1113.41    69.7 1108.12    74.7 1106.94    79.7 1105.77    84.7 1106.82
    89.6 1107.85    99.6 1113.52   109.6 1119.57   119.5 1124.95   129.5 1129.52
   139.5 1132.19   149.4 1133.46   159.4 1135.31   169.3 1138.53   179.3 1142.22
   189.3 1145.86   199.2 1149.13   209.2 1151.26   219.1 1151.68   229.1 1151.42
   239.1 1151.06     249 1150.69
#Mann= 3 , 0 , 0
       0      .1       0    74.7    .045       0    84.7      .1       0
Bank Sta=74.7,84.7
XS Rating Curve= 0 ,0
Exp/Cntr=0.3,0.1

Type RM Length L Ch R = 1 ,3242.8  ,244.9,256.2,267.4
XS GIS Cut Line= 3
     1723853.787      180747.634     1723803.414      180874.499
     1723753.042      181001.365
#Sta/Elev= 30
     9.7 1118.94    19.5 1117.42    29.3 1117.25      39 1117.39    48.8 1117.55
    58.5 1117.63    68.2 1117.57      78 1116.62    87.8 1113.47    97.5    1108
   107.3 1101.38     117 1093.79   126.7 1086.98   131.5 1085.26   136.5 1083.48
   141.5 1084.02   146.2 1084.53     156 1089.59   165.7 1096.16   175.5 1102.17
   185.2 1107.49     195 1112.17   204.7 1114.63   214.5 1115.37   224.2 1117.29
     234 1120.78   243.7 1125.09   253.5 1129.69   263.2 1134.16     273 1138.15
#Mann= 3 , 0 , 0
       0      .1       0   131.5    .045       0   141.5      .1       0
Bank Sta=131.5,141.5
XS Rating Curve= 0 ,0
Exp/Cntr=0.3,0.1

Type RM Length L Ch R = 1 ,2986.6  ,110.8,113.8,116.8
XS GIS Cut Line= 2
      1723697.64      180662.097     1723515.547      180798.667
#Sta/Elev= 25
     9.9 1120.48    19.8 1116.25    29.7 1112.83    39.6 1111.14    49.5 1110.48
    59.4 1109.95    69.3 1109.25    79.2 1106.86    89.1 1103.07      99 1095.91
   108.9 1085.04   118.8 1074.45   123.7 1074.17   128.7  1073.9   133.7 1078.28
   138.5 1082.49   148.4 1094.56   158.3 1101.51   168.2 1104.14   178.1  1105.8
     188  1106.9   197.9 1107.23   207.8 1107.14   217.7 1107.02   227.6 1106.81
#Mann= 3 , 0 , 0
       0     .08       0   123.7    .045       0   133.7     .08       0
Bank Sta=123.7,133.7
XS Rating Curve= 0 ,0
Exp/Cntr=0.3,0.1

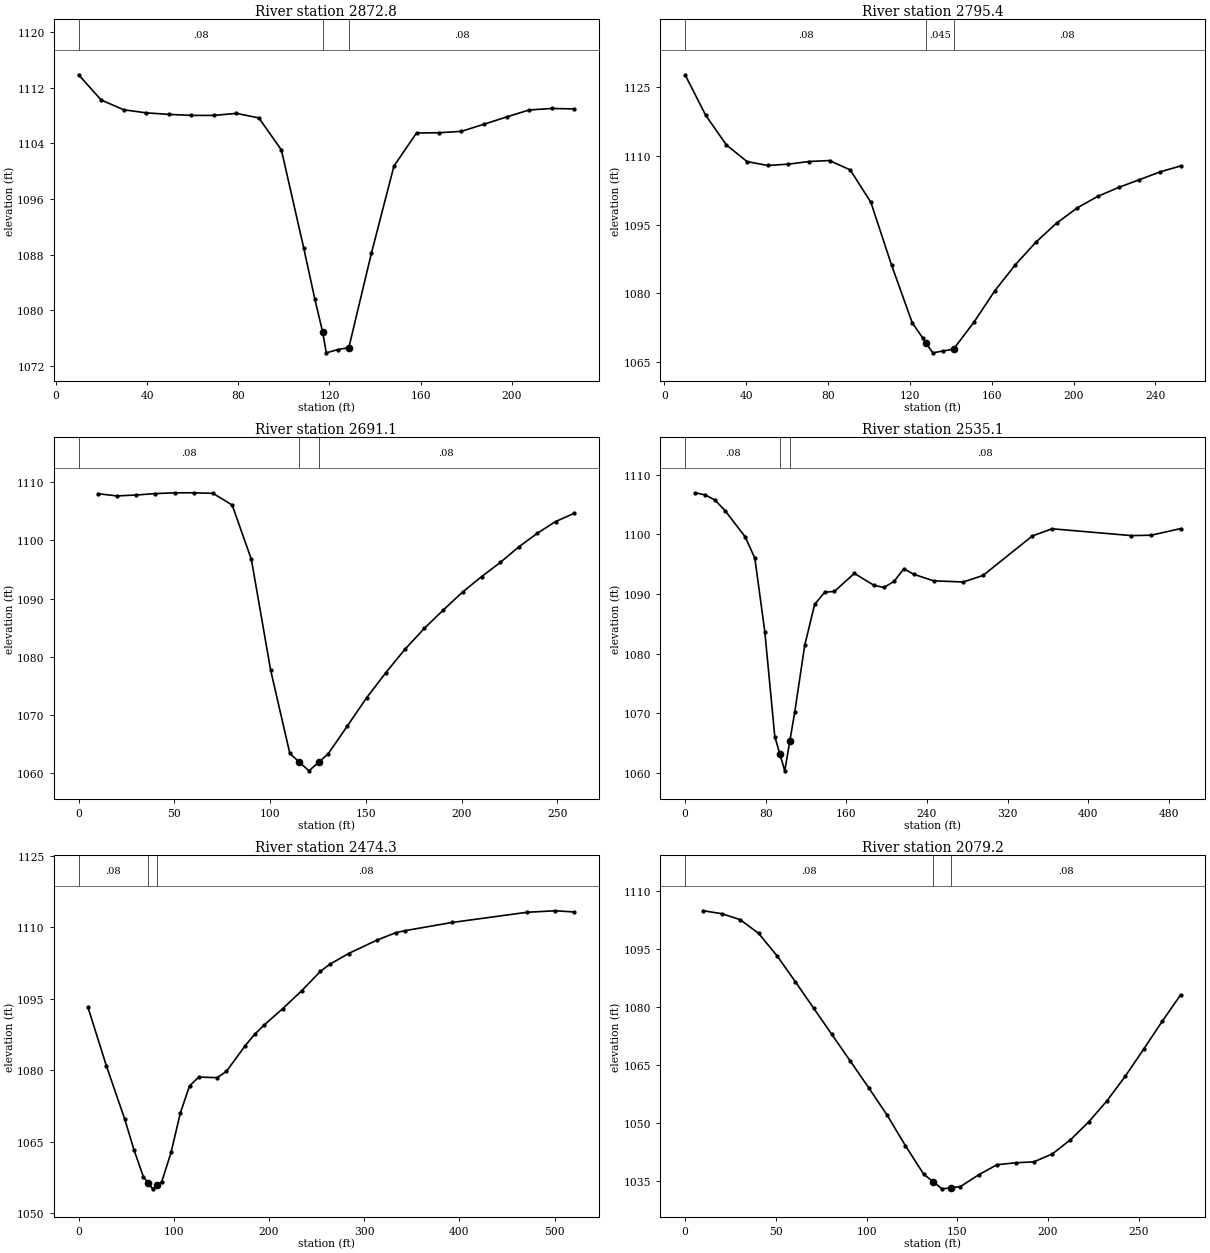
Type RM Length L Ch R = 1 ,2872.8  ,79.5,77.3,75.2
XS GIS Cut Line= 2
     1723656.902       180575.59     1723456.597      180683.192
#Sta/Elev= 26
     9.9 1113.85    19.8 1110.22    29.7 1108.82    39.5 1108.38    49.4 1108.16
    59.3 1108.01    69.2 1108.01    79.1  1108.3      89 1107.65    98.9 1103.04
   108.7 1088.94   113.6 1081.57  117.03 1076.83   118.6 1073.88   123.6 1074.34
   128.5 1074.64   138.4 1088.19   148.3 1100.73   158.2 1105.48   168.1 1105.52
   177.9 1105.72   187.8 1106.74   197.7 1107.78   207.6 1108.79   217.5 1109.01
   227.4 1108.94
#Mann= 3 , 0 , 0
     9.9     .08       0  117.03    .045       0   128.5     .08       0
Bank Sta=117.03,128.5
XS Rating Curve= 0 ,0
Exp/Cntr=0.3,0.1

Type RM Length L Ch R = 1 ,2795.4  ,101.2,104.3,107.4
XS GIS Cut Line= 2
      1723622.09      180490.658     1723413.846      180633.039
#Sta/Elev= 28
    10.1 1127.74    20.2 1118.86    30.3  1112.4    40.4 1108.76    50.5 1107.91
    60.5  1108.2    70.6 1108.78    80.7 1108.99    90.8 1106.94   100.9 1099.86
     111 1086.14   121.1 1073.55   126.2 1070.22  127.85 1069.04   131.2 1066.95
   136.2 1067.36   141.3 1067.77   151.4 1073.73   161.5 1080.53   171.5  1086.2
   181.6 1091.16   191.7 1095.32   201.8 1098.65   211.9 1101.18     222 1103.11
   232.1  1104.8   242.2  1106.5   252.3 1107.81
#Mann= 3 , 0 , 0
    10.1     .08       0  127.85    .045       0   141.3     .08       0
Bank Sta=127.85,141.3
XS Rating Curve= 0 ,0
Exp/Cntr=0.3,0.1

Type RM Length L Ch R = 1 ,2691.1  ,154,156.1,158.1
XS GIS Cut Line= 3
     1723570.756      180421.889     1723380.914      180512.936
     1723372.197      180560.396
#Sta/Elev= 28
      10 1108.04    20.1 1107.66    30.1 1107.82    40.1 1108.06    50.1 1108.19
    60.2  1108.2    70.2  1108.1    80.2 1106.09    90.2 1096.76   100.3 1077.68
   110.3 1063.39   115.3 1061.89   120.3  1060.4   125.3 1061.86   130.3 1063.31
   140.4 1068.14   150.4 1072.96   160.4 1077.26   170.4 1081.28   180.5 1084.88
   190.5 1088.06   200.5 1091.13   210.5  1093.8   220.2 1096.22   229.8 1098.88
   239.5 1101.23   249.1 1103.25   258.8 1104.67
#Mann= 3 , 0 , 0
       0     .08       0   115.3    .045       0   125.3     .08       0
Bank Sta=115.3,125.3
XS Rating Curve= 0 ,0
Exp/Cntr=0.3,0.1

Type RM Length L Ch R = 1 ,2535.1  ,54.5,60.7,67
XS GIS Cut Line= 4
     1723493.057      180301.573     1723381.083      180340.971
     1723385.605      180439.293     1723235.778      180669.331
#Sta/Elev= 30
     9.9 1106.96    19.8 1106.61    29.7 1105.74    39.6 1103.98    59.4 1099.62
    69.2    1096    79.1 1083.65      89 1066.05    93.9 1063.22    98.9 1060.32
   103.9 1065.29   108.8 1070.17   118.7 1081.37   128.5 1088.23   138.4 1090.27
   148.2 1090.42   167.9 1093.44   187.6 1091.42   197.4 1091.08   207.3  1092.1
   217.1 1094.21   226.9 1093.29   246.5 1092.19     276    1092   295.6 1093.09
   344.6 1099.72   364.2 1100.92   442.6 1099.78   462.2 1099.84   491.7 1100.95
#Mann= 3 , 0 , 0
       0     .08       0    93.9    .045       0   103.9     .08       0
Bank Sta=93.9,103.9
XS Rating Curve= 0 ,0
Exp/Cntr=0.3,0.1

Type RM Length L Ch R = 1 ,2474.3  ,389.7,395.1,400.5
XS GIS Cut Line= 3
     1723459.762      180274.332     1723294.801      180278.872
     1723148.001      180602.741
#Sta/Elev= 30
     9.7 1093.25    29.1 1080.93    48.5 1069.66    58.2 1063.22      68 1057.62
    72.7 1056.38    77.7 1055.07    82.7 1055.86    87.4 1056.61    97.1 1062.71
   106.8 1070.95   116.5 1076.67   126.2 1078.54   145.6 1078.41   155.3 1079.74
   174.9  1085.1   184.8 1087.49   194.7 1089.43   214.4  1092.9   234.2 1096.63
   253.9 1100.71   263.8 1102.21   283.6 1104.48   313.2 1107.27   332.9 1108.83
   342.8 1109.27   392.2 1110.99   471.2 1113.14   500.9 1113.45   520.6  1113.2
#Mann= 3 , 0 , 0
       0     .08       0    72.7    .045       0    82.7     .08       0
Bank Sta=72.7,82.7
XS Rating Curve= 0 ,0
Exp/Cntr=0.3,0.1

Type RM Length L Ch R = 1 ,2079.2  ,500.7,497.5,494.3
XS GIS Cut Line= 2
     1723591.429      179924.735     1723326.583      179858.145
#Sta/Elev= 29
    10.1 1104.77    20.2 1104.02    30.3 1102.49    40.5 1098.95    50.6 1093.19
    60.7  1086.5    70.8 1079.65    80.9 1072.83      91    1066   101.1 1059.14
   111.3 1052.04   121.4 1044.14   131.5 1036.76   136.6 1034.85   141.6 1032.98
   146.6 1033.26   151.7 1033.55   161.8 1036.61   171.9  1039.2   182.1  1039.7
   192.2 1039.95   202.3 1041.97   212.4 1045.65   222.5 1050.29   232.6 1055.77
   242.7 1062.13   252.9 1069.16     263 1076.28   273.1 1083.07
#Mann= 3 , 0 , 0
       0     .08       0   136.6    .045       0   146.6     .08       0
Bank Sta=136.6,146.6
XS Rating Curve= 0 ,0
Exp/Cntr=0.3,0.1

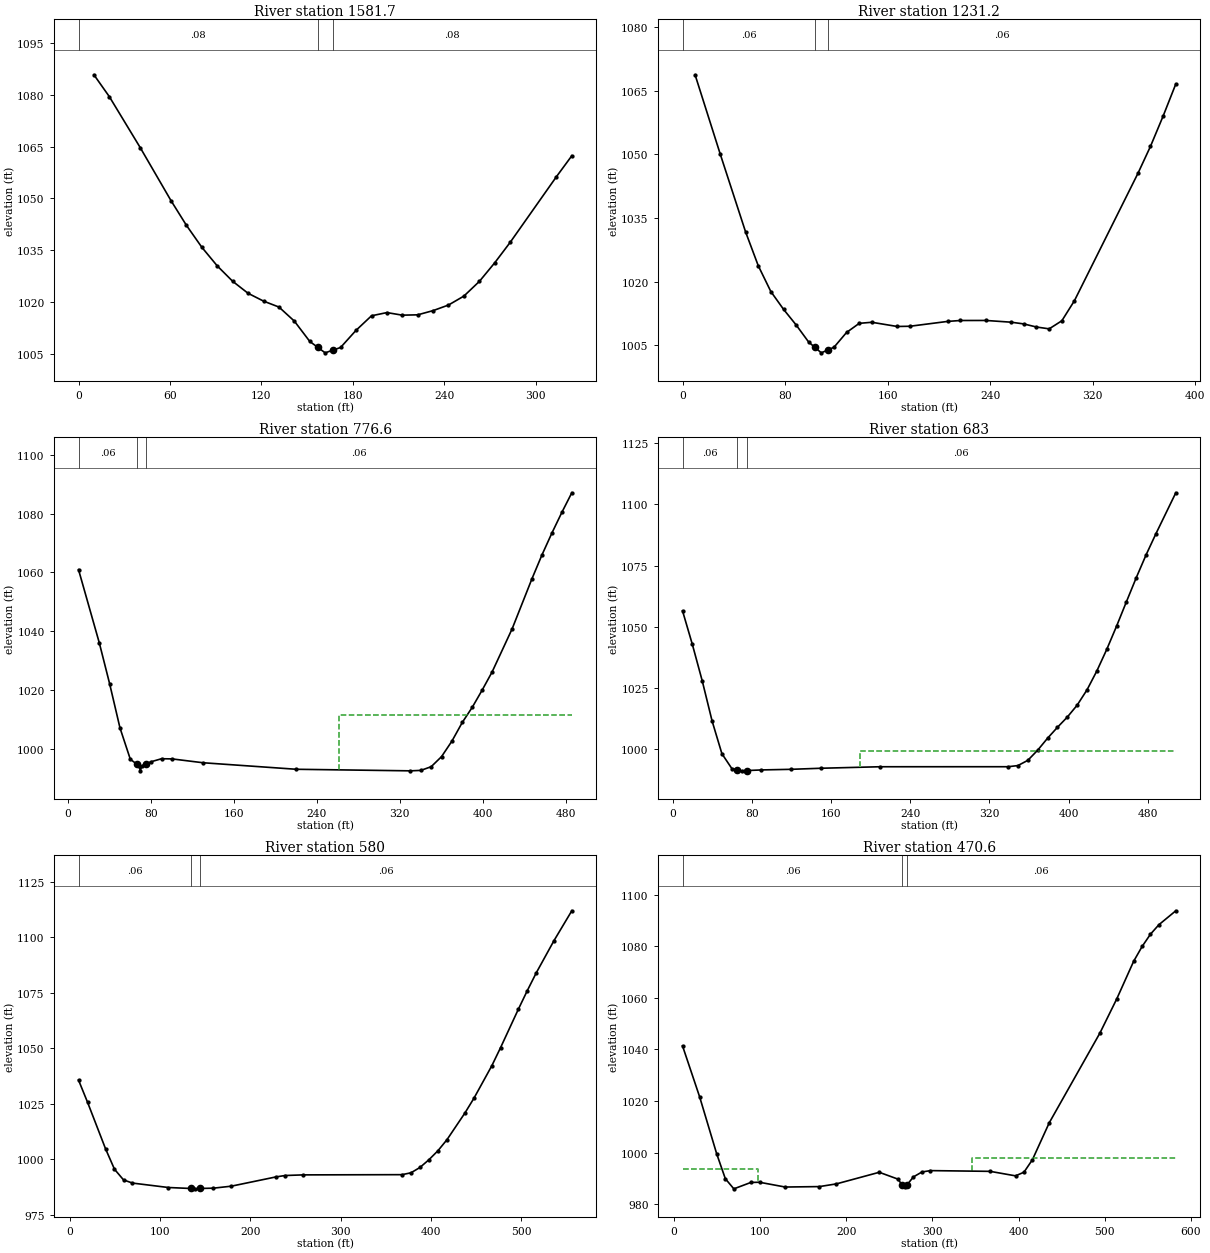
Type RM Length L Ch R = 1 ,1581.7  ,350.5,350.5,350.4
XS GIS Cut Line= 2
     1723735.202      179431.365     1723412.847       179402.61
#Sta/Elev= 30
    10.1 1085.82    20.2 1079.49    40.5 1064.69    60.7 1049.31    70.8 1042.17
    80.9 1035.81      91 1030.42   101.1 1025.96   111.2 1022.48   121.4  1020.2
   131.5 1018.48   141.6  1014.4   151.7 1008.52   156.8 1006.85   161.8 1005.21
   166.8 1005.98   171.9 1006.76     182 1011.71   192.2 1015.95   202.3 1016.88
   212.4 1016.13   222.5 1016.23   232.6 1017.45   242.7 1019.07   252.8 1021.66
     263 1025.94   273.1 1031.35   283.2 1037.26   313.5 1056.27   323.6 1062.34
#Mann= 3 , 0 , 0
       0     .08       0   156.8    .045       0   166.8     .08       0
Bank Sta=156.8,166.8
XS Rating Curve= 0 ,0
Exp/Cntr=0.3,0.1

Type RM Length L Ch R = 1 ,1231.2  ,456.1,454.6,453.1
XS GIS Cut Line= 3
     1723783.631      179096.902      1723636.77      179081.164
     1723406.793      179139.277
#Sta/Elev= 30
     9.8 1068.78    29.5 1050.01    49.2 1031.72    59.1 1023.73    68.9 1017.65
    78.8 1013.46    88.6 1009.78    98.5  1005.7   103.3 1004.47   108.3 1003.18
   113.3 1003.85   118.2  1004.5     128 1007.99   137.9 1010.14   147.7 1010.39
   167.5  1009.4   177.4 1009.45     207  1010.6   216.9 1010.81   236.7 1010.82
   256.4 1010.41   266.3    1010   276.2 1009.27   286.1 1008.84     296 1010.75
   305.8 1015.48   355.3 1045.49   365.1 1051.87     375 1059.03   384.9 1066.61
#Mann= 3 , 0 , 0
       0     .06       0   103.3    .045       0   113.3     .06       0
Bank Sta=103.3,113.3
XS Rating Curve= 0 ,0
Exp/Cntr=0.3,0.1

Type RM Length L Ch R = 1 ,776.6   ,93.6,93.6,93.6
XS GIS Cut Line= 3
     1723845.113      178644.204      1723464.87      178638.529
     1723370.282      178685.823
#Sta/Elev= 30
      10 1060.96      30 1036.14      40 1022.22      50 1007.19      60  996.52
    66.6  994.78   68.48  994.28    69.6  992.63    71.1  994.28   75.11  994.97
    80.1   995.7    90.1  996.71   100.1  996.66   130.1  995.35   220.2  993.13
   330.2   992.6   340.3  992.75   350.3  994.01   360.3  997.43   370.3 1002.69
   380.3 1009.04   389.9 1014.17   399.5 1020.03   409.1  1026.2   428.4 1040.83
   447.6  1057.9   457.2 1065.95   466.8 1073.39   476.4 1080.41     486 1087.06
#Mann= 3 , 0 , 0
      10     .06       0    66.6    .045       0   75.11     .06       0
#XS Ineff= 2 , 0
                          260.91         1011.44
Permanent Ineff=
       F       F
Bank Sta=66.6,75.11
XS Rating Curve= 0 ,0
Exp/Cntr=0.3,0.1

Type RM Length L Ch R = 1 ,683     ,102,103.1,105.7
XS GIS Cut Line= 2
     1723856.746      178551.667     1723348.534       178543.39
#Sta/Elev= 30
      10 1056.57    19.9 1042.92    29.9 1028.01    39.9 1011.57    49.8  998.24
    59.8  992.19    64.8  991.72    69.8  991.25    74.8  991.36    89.7  991.62
   119.6  991.87   149.5   992.3   209.3  992.92   338.9  992.93   348.8   993.4
   358.8  995.53   368.8   999.7   378.7 1004.54   388.7    1009   398.7 1013.19
   408.6 1018.03   418.6  1024.3   428.5 1031.99   438.5 1040.78   448.5 1050.34
   458.4 1060.26   468.4 1070.14   478.4 1079.52   488.3 1088.11   508.3 1104.75
#Mann= 3 , 0 , 0
      10     .06       0    64.8    .045       0    74.8     .06       0
#XS Ineff= 2 , 0
                          189.71          999.17
Permanent Ineff=
       F       F
Bank Sta=64.8,74.8
XS Rating Curve= 0 ,0
Exp/Cntr=0.3,0.1

Type RM Length L Ch R = 1 ,580     ,113.4,109.3,103.6
XS GIS Cut Line= 3
     1723883.739       178456.87     1723426.583      178469.569
     1723337.691      178511.898
#Sta/Elev= 30
     9.9 1035.65    19.9 1025.63    39.8 1004.67    49.7  995.45    59.7  990.64
    69.6  989.21   109.4  987.21   134.2  986.77  139.18  986.61   144.2  986.78
   159.1  986.91     179  987.81   228.7  992.01   238.6  992.62   258.5   992.9
   367.9     993   377.8  993.84   387.7  996.23   397.7  999.74   407.6 1003.77
   417.6 1008.74   437.4 1020.73   447.4 1027.39   467.2 1042.04     477  1050.3
   496.7 1067.63   506.6 1076.01   516.4 1083.94   536.1 1098.52   555.8 1111.96
#Mann= 3 , 0 , 0
     9.9     .06       0   134.2    .045       0   144.2     .06       0
Bank Sta=134.2,144.2
XS Rating Curve= 0 ,0
Exp/Cntr=0.3,0.1

Type RM Length L Ch R = 1 ,470.6   ,55,57.7,60.5
XS GIS Cut Line= 3
     1723893.052      178343.334     1723550.066      178398.981
     1723327.109      178473.802
#Sta/Elev= 30
     9.9 1041.39    29.8 1021.62    49.6  999.56    59.6  989.95    69.5  986.02
    89.3   988.5    99.3  988.57   129.1  986.72   168.8  986.89   188.6  987.94
   238.3  992.43     260 989.784  265.04  987.43  268.32  986.59  270.37  987.49
     278  990.65   287.9  992.55   297.8  993.08   367.1  992.79   396.5  991.05
   406.3  992.46   416.1  997.28   435.7 1011.62   494.5 1046.35   514.1 1059.62
   533.7 1074.17   543.5 1079.88   553.2 1084.64     563 1088.31   582.6  1093.7
#Mann= 3 , 0 , 0
     9.9     .06       0  265.04    .045       0  270.37     .06       0
#XS Ineff= 2 , 0
           97.65  993.73  346.17          998.08
Permanent Ineff=
       F       F
Bank Sta=265.04,270.37
XS Rating Curve= 0 ,0
Exp/Cntr=0.3,0.1

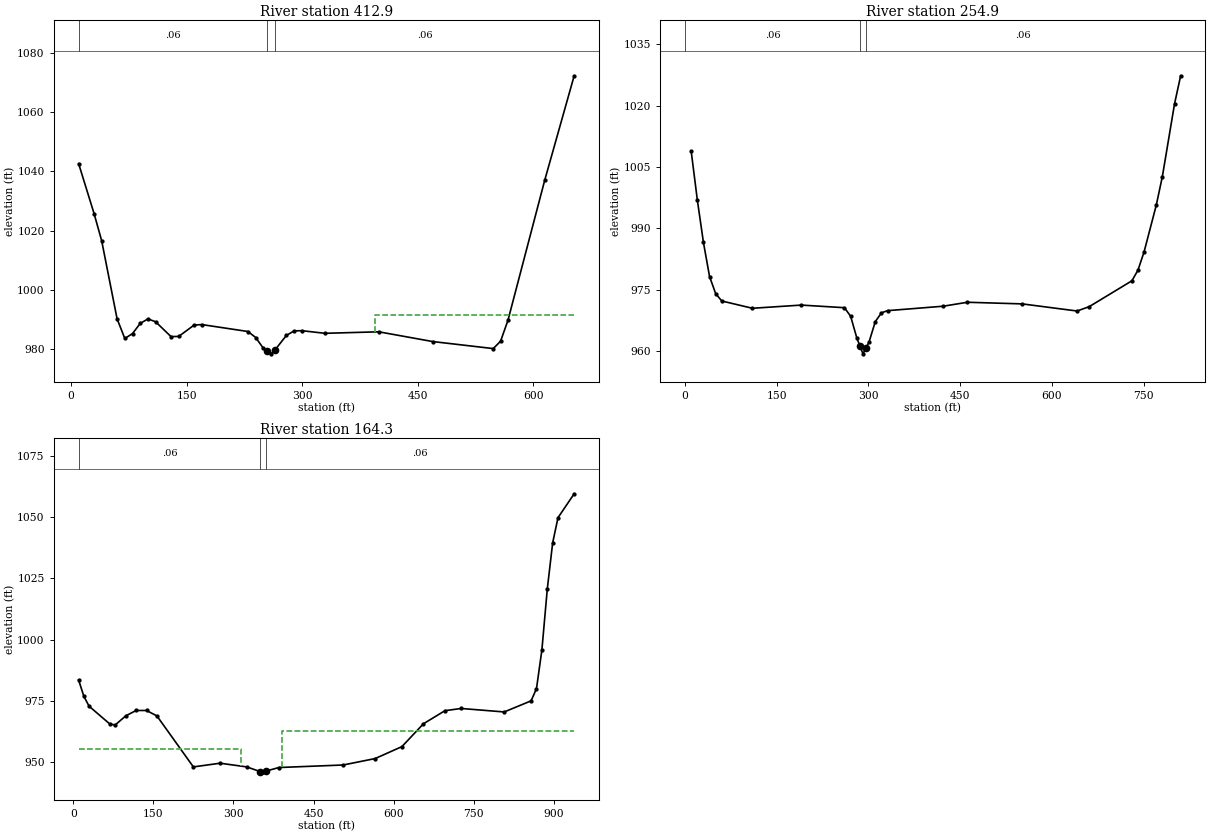
Type RM Length L Ch R = 1 ,412.9   ,158.1,158,157.9
XS GIS Cut Line= 3
     1723896.191      178324.497     1723377.055      178336.252
     1723305.962      178449.353
#Sta/Elev= 30
      10 1042.64      30 1025.76    39.9 1016.52    59.9  990.09    69.9  983.45
    79.9   985.1    89.9  988.55    99.9  990.07   109.8  989.12   129.8  984.09
   139.8  984.14   159.8  987.98   169.8  988.16   229.7  985.81   239.7  983.78
   249.6  980.14   254.6   979.2   259.6  978.25   264.6  979.52   279.6   984.5
   289.6  986.02   299.6  986.09   329.5   985.2   399.4  985.71   469.3  982.41
   547.9  980.03   557.4  982.52     567   989.6   614.7 1037.04   652.9 1072.39
#Mann= 3 , 0 , 0
      10     .06       0   254.6    .045       0   264.6     .06       0
#XS Ineff= 2 , 0
                          394.63          991.44
Permanent Ineff=
       F       F
Bank Sta=254.6,264.6
XS Rating Curve= 0 ,0
Exp/Cntr=0.3,0.1

Type RM Length L Ch R = 1 ,254.9   ,90.6,90.6,90.5
XS GIS Cut Line= 4
     1723883.694      178294.428     1723739.673      178170.271
     1723507.914      178176.893     1723147.034      178320.914
#Sta/Elev= 30
      10 1008.85      20  996.99      30  986.58      40  978.25      50  974.07
      60  972.27   110.1  970.49   190.1  971.27   260.7  970.63   270.8  968.53
   280.9  963.23     286  961.27     291  959.35     296  960.82     301  962.29
   311.1  967.22   321.2  969.38   331.3  969.91     422  970.99   461.9  971.96
   551.5  971.56   641.2  969.82   661.1  970.89   730.9  977.21   740.8  979.81
   750.8  984.28   770.7  995.67   780.7 1002.69   800.6 1020.45   810.6 1027.33
#Mann= 3 , 0 , 0
       0     .06       0     286    .045       0     296     .06       0
Bank Sta=286,296
XS Rating Curve= 0 ,0
Exp/Cntr=0.3,0.1

Type RM Length L Ch R = 1 ,164.3   ,182.3,164.3,146.4
XS GIS Cut Line= 5
     1723885.349      178256.353     1723805.889      178183.515
     1723752.916      178079.224     1723362.238      178090.812
     1723095.716      178272.907
#Sta/Elev= 30
     9.8  983.46    19.6  976.83    29.4  972.79    68.6  965.47    78.4  965.15
      98  968.84   117.5  971.05     137  971.05   156.5  968.83   224.8  948.03
   274.9  949.54     325  948.03     350  946.12     355  946.02     360  946.28
   385.1  947.78   505.4  948.81   565.5  951.44   615.6  956.31     656  965.64
   696.3  970.97   726.6  971.87   807.3  970.45   857.7  974.98   867.8  979.99
   877.9  995.72     888 1020.55   898.1 1039.44   908.1 1049.71   938.4 1059.45
#Mann= 3 , 0 , 0
     9.8     .06       0     350    .045       0     360     .06       0
#XS Ineff= 2 , 0
           314.7   955.4  391.79          962.88
Permanent Ineff=
       F       F
Bank Sta=350,360
XS Rating Curve= 0 ,0
Exp/Cntr=0.3,0.1
Stream Node=War Branch      ,Main            , 0 , 0 ,Upstream end
Stream Node=War Branch      ,Main            , 0 , 1 ,Downstream end

Chan Stop Cuts=-1
Use User Specified Reach Order=0